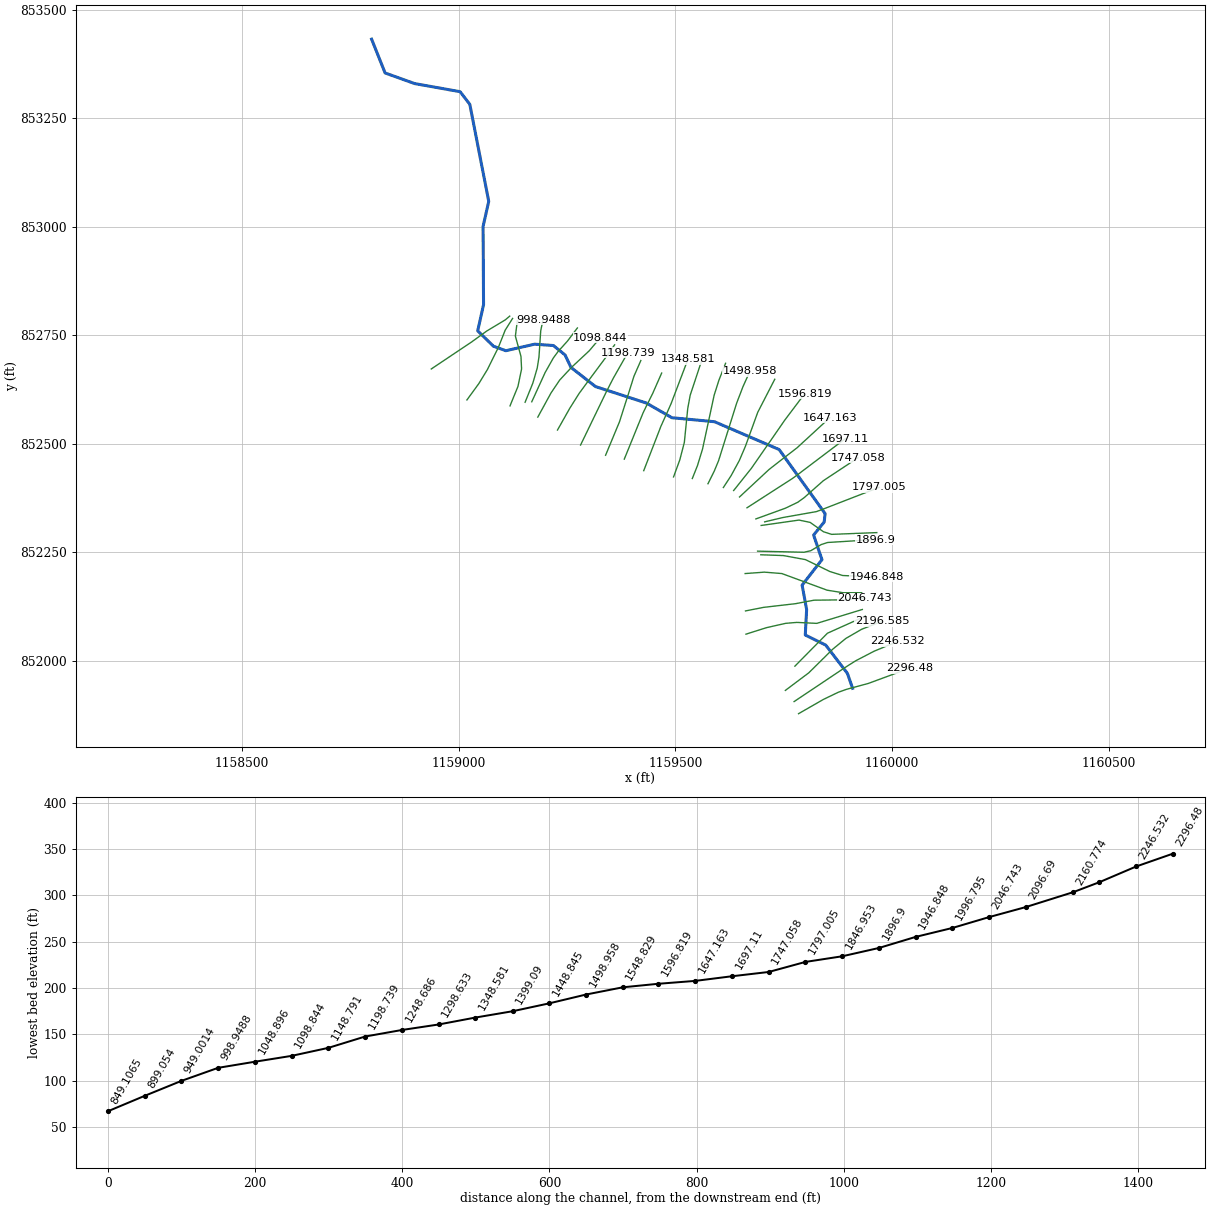
--- 184_ras.prj (project) ---

Proj Title=184
Current Plan=p01
Default Exp/Contr=0.3,0.1
English Units
Geom File=g01
Flow File=f01
Plan File=p01
Y Axis Title=Elevation
X Axis Title(PF)=Main Channel Distance
X Axis Title(XS)=Station
BEGIN DESCRIPTION:
RFD model 184 exported to HEC-RAS
END DESCRIPTION:

--- 184_ras.p01 (plan) ---

Plan Title=Plan 01
Program Version=4.10
Short Identifier=Plan 01
Geom File=g01
Flow File=f01
Subcritical Flow
Calc Critical at every XS
Secant Critical Depth

--- 184_ras.f01 (steady flow) ---

Flow Title=Flow 01
Program Version=5.01
Number of Profiles= 5
Profile Names=10yr,25yr,50yr,100yr,500yr
River Rch & RM=184,41, 2296.48
  278.32   503.9  729.12 1006.73 1875.36
River Rch & RM=184,41,2246.532
  308.04  558.96  810.51 1121.68 2102.41
River Rch & RM=184,41, 2096.69
  323.18  587.03  852.07 1180.48 2219.08
River Rch & RM=184,41,1996.795
  324.99   590.4  857.06 1187.54 2233.12
River Rch & RM=184,41,1797.005
  332.85  604.99  878.69 1218.17 2294.03
River Rch & RM=184,41,1647.163
  354.58  645.39  938.61  1303.1 2463.43
River Rch & RM=184,41,1498.958
  365.43  665.58  968.59 1345.64 2548.51
River Rch & RM=184,41, 1399.09
  377.48  688.01 1001.91 1392.96 2643.33
River Rch & RM=184,41,1298.633
  385.91  703.71 1025.25 1426.12 2709.88
River Rch & RM=184,41,1198.739
  393.13  717.16 1045.25 1454.56 2767.03
River Rch & RM=184,41,1098.844
  395.53  721.65 1051.92 1464.04 2786.11
River Rch & RM=184,41,998.9488
  404.55  738.46 1076.94 1499.63 2857.73
River Rch & RM=184,41, 899.054
  441.15  806.81 1178.76 1644.63 3150.58
River Rch & RM=184,41,699.2642
  446.54  816.89 1193.79 1666.06 3193.99
River Rch & RM=184,41,599.3693
  447.74  819.13 1197.13 1670.82 3203.65
River Rch & RM=184,41,399.5795
  477.06  873.99 1279.01 1787.67 3440.93
River Rch & RM=184,41, 276.865
  483.64   886.3  1297.4 1813.94  3494.4
River Rch & RM=184,41,136.6749
  495.59  908.69 1330.85 1861.73 3591.78
River Rch & RM=184,41,  47.009
  505.74  927.71 1359.29 1902.39 3674.74
Boundary for River Rch & Prof#=184,41,1
Up Type= 0
Dn Type= 2
Boundary for River Rch & Prof#=184,41,2
Up Type= 0
Dn Type= 2
Boundary for River Rch & Prof#=184,41,2
Up Type= 0
Dn Type= 2
Boundary for River Rch & Prof#=184,41,2
Up Type= 0
Dn Type= 2
Boundary for River Rch & Prof#=184,41,2
Up Type= 0
Dn Type= 2

--- 184_ras.g01 (geometry) ---

Geom Title=184
Program Version=4.10

River Reach=184,41
Reach XY= 30
1159908.98810026851936.8858802911159897.03531009851971.185194358
1159847.14540097852036.1460172831159799.85392353852059.531914398
1159802.97204465852118.2564968911159792.57831484852174.382646948
1159838.31073493852233.1072282341159819.08233336852289.753065109
1159843.50760311 852319.894885541159845.58634996852339.123288631
1159739.57029337852486.7142780871159590.50064683852550.796636075
1159492.19948691852559.9900917711159433.47490519852593.769720644
1159316.02574083852631.7068438081159259.37990567852675.880204022
1159245.86805561852704.4629658311159218.84435445852726.289802611
1159175.71036908852729.4079232961159109.19048733852714.337014645
 1159080.6077261852724.7307468951159044.22966704852760.069434777
1159057.74151966852820.3530767561159056.70215169853000.684317157
1159069.69431767853058.3695262671159026.04065198853281.834753379
1159003.69413021853310.9372020211158898.71744308853329.645921618
1158830.63850278853354.0711924431158799.45731068853432.024179101

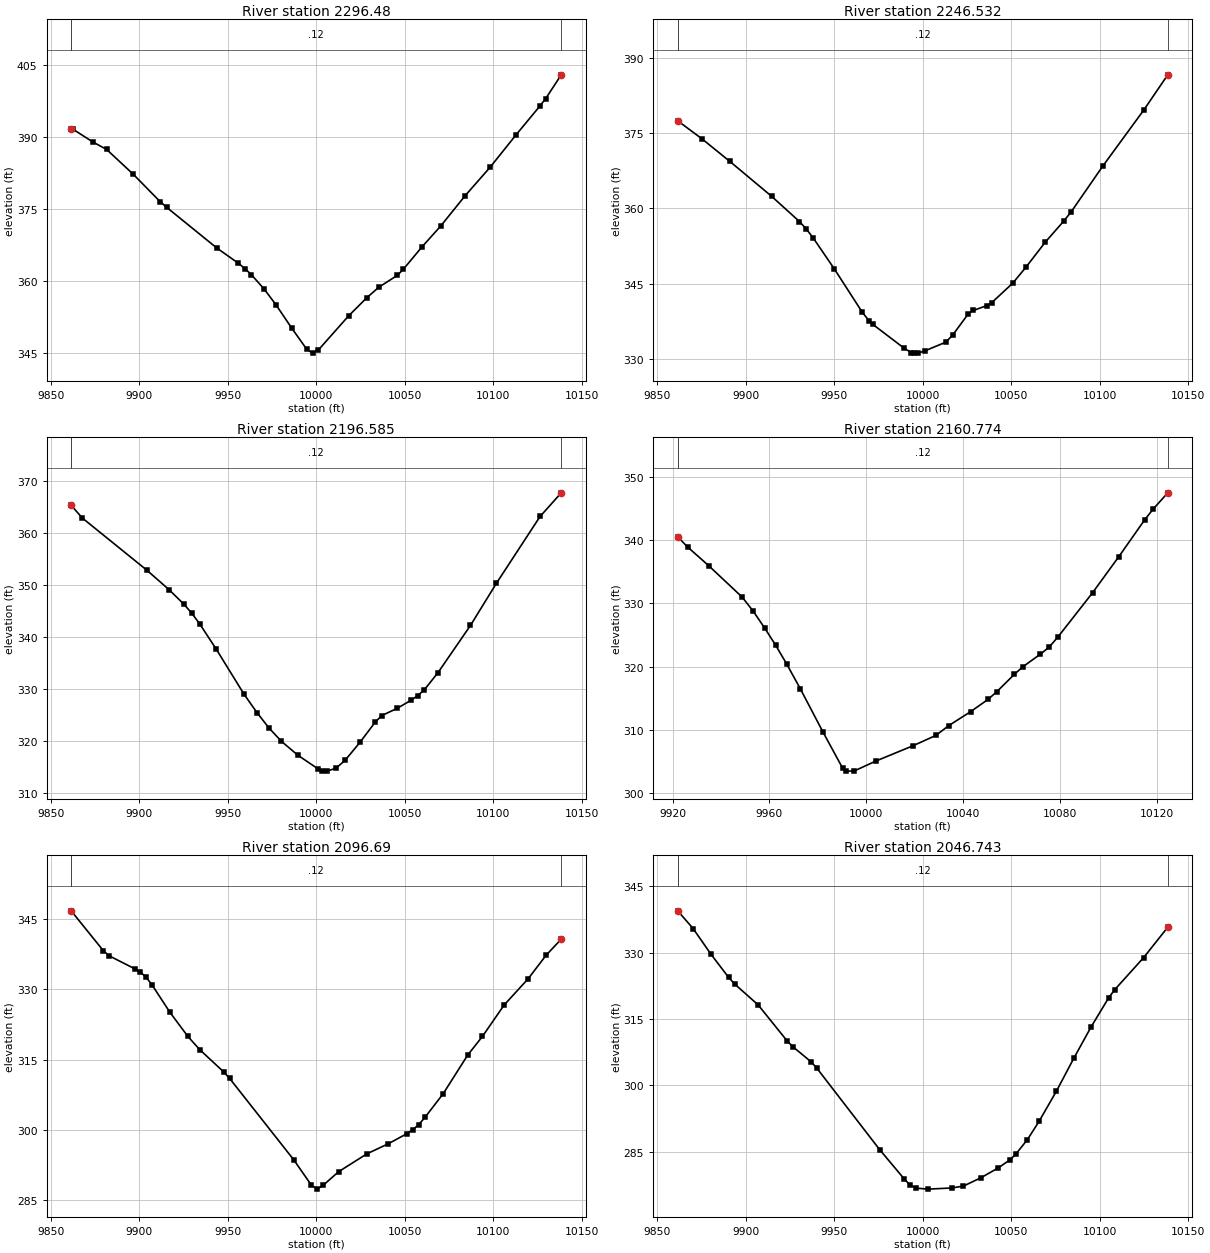
Type RM Length L Ch R = 1 , 2296.48,49.947400,49.947400,49.947400
XS GIS Cut Line= 6
1159784.40077246851878.3514745431159841.40596801851911.015086977
1159875.89784178851927.6335004991159895.28032803 851934.52230345
1159945.21527008851947.9472548551160039.67296043851982.761188364
#Sta/Elev= 30
9861.533391.64019862.649391.53349873.993388.86629881.555387.3625 9896.68382.1791
9911.805376.50569915.586375.2931 9943.69366.90799956.076363.67929959.717362.5864
9963.359361.31339970.418358.40799977.382 355.0049986.256350.15449994.542345.8745
9997.924345.009810001.29345.691610018.32352.757910028.54356.510510035.35358.7038
10045.77361.163610049.27 362.45810059.76367.093210070.25371.389210084.23377.7709
10098.22383.632310112.94390.399210126.19396.290110129.69397.942210138.47402.8732
#Mann= 3 , 0 , 0
9861.533    0.12       09861.533    0.12       010138.47    0.12       0
#XS Ineff= 2 , 0
       0                               0
Bank Sta=9861.533,10138.47
Exp/Cntr=0.3,0.1

Type RM Length L Ch R = 1 ,2246.532,49.947500,49.947500,49.947500
XS GIS Cut Line= 6
1159774.07395758851906.184381411 1159888.3952508851982.572082866
1159890.06919006851983.6665815431159915.74300013851999.931319464
1159958.71817585852022.2615223151160012.90377379852044.677277611
#Sta/Elev= 30
9861.507377.48299875.091373.92629890.874369.41699914.549362.44199930.333357.3911
9934.278355.87569938.224354.05749950.062347.93719965.845339.29899969.791 337.558
9971.639336.9296 9989.52332.13229993.466331.2835 9995.26331.16169997.412331.1718
   10001331.582410012.99333.345110016.87334.736810025.72338.988210028.53339.6646
10036.06340.611610039.05341.243810050.85345.106910058.24348.258110069.33353.3275
10079.82357.544110083.95359.3674 10101.7368.428610125.05379.696910138.46 386.647
#Mann= 3 , 0 , 0
9861.507    0.12       09861.507    0.12       010138.46    0.12       0
#XS Ineff= 2 , 0
       0                               0
Bank Sta=9861.507,10138.46
Exp/Cntr=0.3,0.1

Type RM Length L Ch R = 1 ,2196.585,35.810300,35.810300,35.810300
XS GIS Cut Line= 6
1159753.93826573851931.9407138141159807.90413177851972.427967199
1159863.07164584 852026.778399371159893.28967193852051.557439468
 1159929.8457194852072.7163840891159976.95867842852091.174345783
#Sta/Elev= 30
9861.533365.25199867.882362.8039 9904.26352.80879916.923349.03679925.365346.2178
9929.637344.56119934.246342.43779943.464 337.6569959.202328.9894 9966.51325.4624
9973.215322.53899980.337319.94619989.555317.2985   10001314.660610003.36314.3289
10005.97314.232610011.09314.782810016.27316.302810024.79319.803210033.27323.6272
10036.96324.892210045.55326.255310053.54327.836710057.33  328.7310061.12329.8789
 10068.7333.107610087.08342.186810101.76350.288110126.42 363.11110138.39367.6537
#Mann= 3 , 0 , 0
9861.533    0.12       09861.533    0.12       010138.39    0.12       0
#XS Ineff= 2 , 0
       0                               0
Bank Sta=9861.533,10138.39
Exp/Cntr=0.3,0.1

Type RM Length L Ch R = 1 ,2160.774,64.084600,64.084600,64.084600
XS GIS Cut Line= 3
1159775.91731349851987.7758027461159850.98550704852063.663680285
1159938.41731349852102.879969418
#Sta/Elev= 30
9922.052340.56139926.162338.95459934.884335.98119948.728330.99989953.343328.7324
9957.958326.13339962.573323.35369967.188320.34569972.813316.41569982.144309.5814
9990.262303.85889991.474 303.4249994.876303.408610004.11305.029210019.47307.4577
 10028.8309.076110034.01310.605710043.18312.850610050.37314.796310053.97316.0099
10061.16318.736910064.75319.965110071.94  321.9510075.54323.055910079.14324.6458
10093.52331.687810104.31337.379710115.09343.268310118.69345.013910124.62347.5439
#Mann= 3 , 0 , 0
9922.052    0.12       09922.052    0.12       010124.62    0.12       0
#XS Ineff= 2 , 0
       0                               0
Bank Sta=9922.052,10124.62
Exp/Cntr=0.3,0.1

Type RM Length L Ch R = 1 , 2096.69,49.947400,49.947400,49.947400
XS GIS Cut Line= 6
1159663.11192272852061.5029724741159710.59025315852076.500225743
1159754.74384692852086.4173156311159779.99035085852088.557314355
1159826.40544526852086.3375727041159931.38391668852118.298997499
#Sta/Elev= 30
9861.583346.72929879.694338.25779883.134337.12459897.619334.35459900.338333.7491
9903.778332.65189907.219330.96219917.401325.08039927.488319.96849934.214317.1385
9947.664312.41999951.026311.04039987.366293.62979997.252288.264210000.57287.4106
10003.88288.211710012.73291.146910028.63294.933710040.69 297.07710051.05299.1969
10054.51 300.05910057.96301.182810061.41302.692910071.78307.779310085.59 315.996
 10093.9319.961810106.11 326.635 10119.7332.243310129.89337.276510138.41340.6894
#Mann= 3 , 0 , 0
9861.583    0.12       09861.583    0.12       010138.41    0.12       0
#XS Ineff= 2 , 0
       0                               0
Bank Sta=9861.583,10138.41
Exp/Cntr=0.3,0.1

Type RM Length L Ch R = 1 ,2046.743,49.947400,49.947400,49.947400
XS GIS Cut Line= 6
1159661.99695058852115.0185726021159703.89050546852123.229129914
1159777.40436816852131.709905972 1159820.2139259852139.734470162
1159894.42379682 852140.609036051159936.69401546852144.434803323
#Sta/Elev= 30
 9861.53339.47259870.236335.47859880.265329.70389890.295324.43199893.638322.9608
9906.977318.2189 9923.49310.01559926.793308.69789936.701305.42059940.003303.9965
9975.627285.5149 9989.67278.8116 9993.01 277.442 9996.35276.799110003.05276.5785
10016.38276.837510023.02277.272210032.87279.149410042.71281.387610049.27283.1982
10052.55284.475410059.12287.763810065.68291.863610075.52298.716810085.36306.1588
10095.21313.302110105.09319.843710108.38321.610310124.85328.923110138.44335.7711
#Mann= 3 , 0 , 0
 9861.53    0.12       0 9861.53    0.12       010138.44    0.12       0
#XS Ineff= 2 , 0
       0                               0
Bank Sta=9861.53,10138.44
Exp/Cntr=0.3,0.1

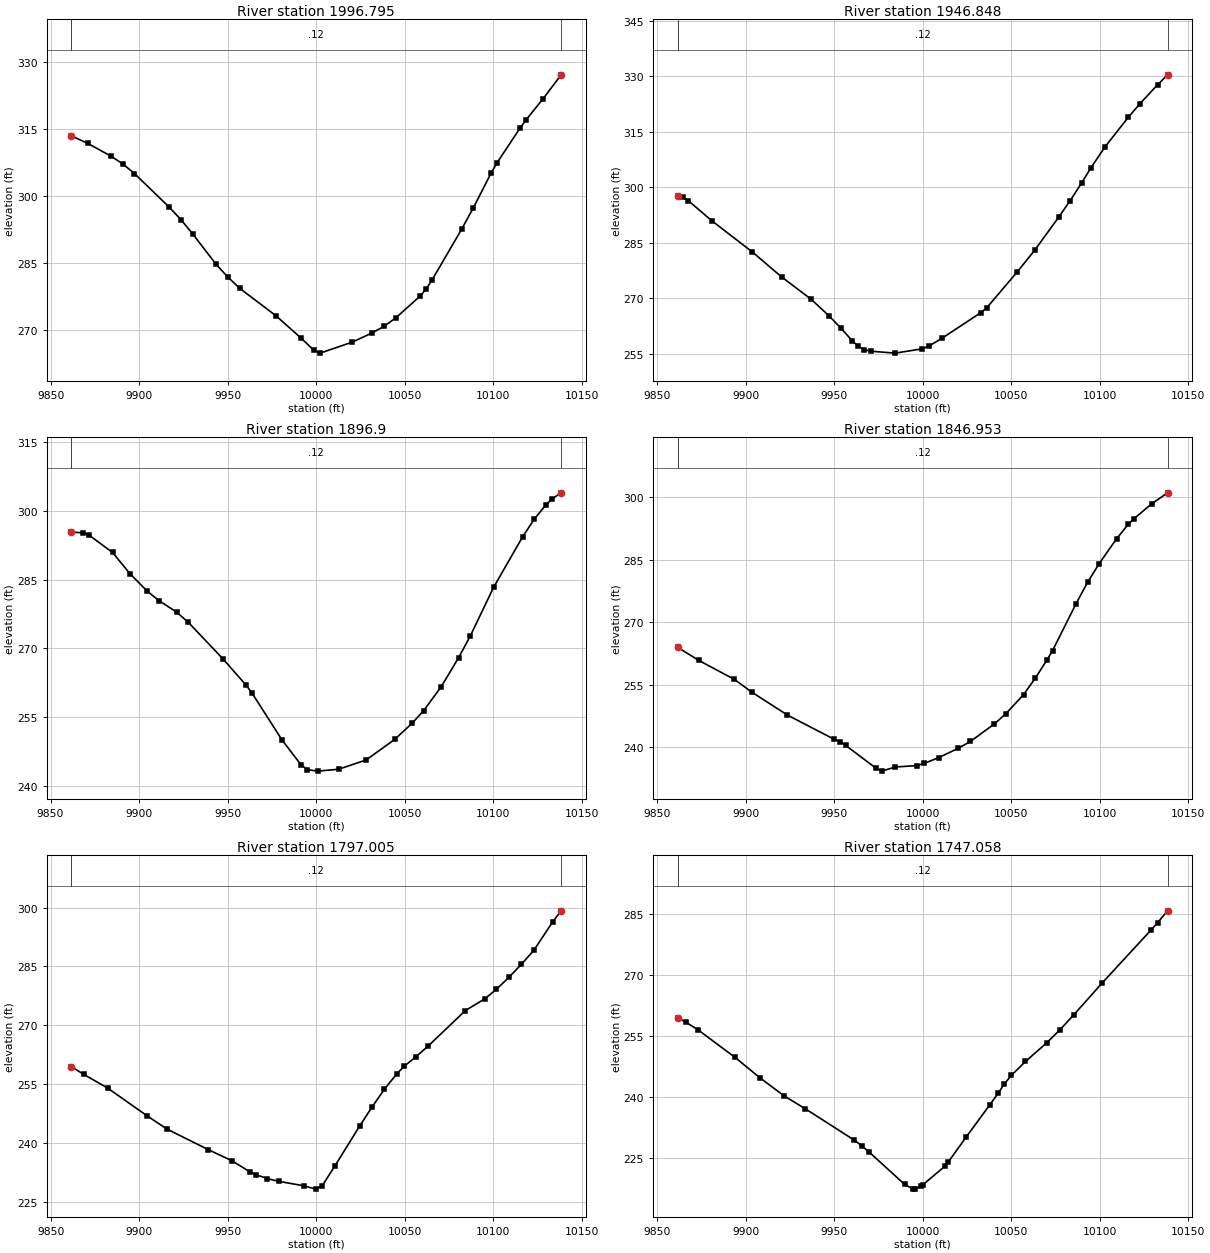
Type RM Length L Ch R = 1 ,1996.795,49.947500,49.947500,49.947500
XS GIS Cut Line= 6
1159661.13010094852201.0691340921159705.59647231852204.314932086
1159745.87088913852201.0614529971159850.41051559852162.735470558
1159887.00513322852156.9386919981159930.01140466852156.932406552
#Sta/Elev= 30
9861.631313.50619871.066311.78079884.224308.91719890.803307.19119897.382305.0445
9917.126297.47389923.709294.69099930.292291.51069943.458284.73569950.143281.8505
9956.921279.3095 9977.28273.21099991.533268.19159998.659265.492910002.23264.8332
10020.53267.310210031.34269.312810038.24270.799310045.13272.7698 10058.9277.6695
10062.22279.226810065.54281.254110082.15292.5614 10088.8297.372110098.72305.0671
   10102307.358210115.12315.177910118.41 316.98610128.25321.824910138.38327.1484
#Mann= 3 , 0 , 0
9861.631    0.12       09861.631    0.12       010138.38    0.12       0
#XS Ineff= 2 , 0
       0                               0
Bank Sta=9861.631,10138.38
Exp/Cntr=0.3,0.1

Type RM Length L Ch R = 1 ,1946.848,49.947400,49.947400,49.947400
XS GIS Cut Line= 6
1159697.25555298852244.3179558421159749.51098001852242.486729879
1159800.28902604852233.1870186571159856.49828571852205.761385274
1159886.28315167852196.5531258281159964.92532116852193.420688412
#Sta/Elev= 30
9861.591297.51199864.403 297.3379867.684296.36499880.807 290.9929903.819282.5126
9920.362 275.7739937.039269.73299947.045265.28989953.716262.02379960.387258.4404
9963.722257.01899967.123256.11839970.604255.70659984.525255.1902 9999.67256.3378
10003.37257.044910010.83259.168610032.81266.100310036.25267.448610053.42277.1116
10063.56283.149410076.77291.845810083.38296.402310089.98301.276210095.06305.2543
10103.15310.980910116.27318.947210122.84 322.61410132.68327.659210138.36330.3659
#Mann= 3 , 0 , 0
9861.591    0.12       09861.591    0.12       010138.36    0.12       0
#XS Ineff= 2 , 0
       0                               0
Bank Sta=9861.591,10138.36
Exp/Cntr=0.3,0.1

Type RM Length L Ch R = 1 ,  1896.9,49.947500,49.947500,49.947500
XS GIS Cut Line= 6
 1159689.8337917852252.6792638151159796.77416954852250.136048694
1159812.51902601 852253.675429171159836.52065242852267.818229529
1159851.30431273852272.6053548551159961.18819888852279.389487145
#Sta/Elev= 30
9861.662295.36029868.619295.19919871.902294.66189885.034290.92079894.883286.2824
9904.737282.43939911.308280.41249921.164277.91379927.735275.72239947.447267.6947
9960.589261.92319963.874260.21469980.574250.12669991.349244.67339995.111243.5532
   10001 243.23710012.73243.648810028.27245.669810044.37250.148610054.23 253.678
 10060.8256.445410070.65261.6488 10080.5267.981210087.07272.708210100.21283.3023
10116.68294.360610123.26298.216810129.85301.323410133.15302.562610138.38303.9261
#Mann= 3 , 0 , 0
9861.662    0.12       09861.662    0.12       010138.38    0.12       0
#XS Ineff= 2 , 0
       0                               0
Bank Sta=9861.662,10138.38
Exp/Cntr=0.3,0.1

Type RM Length L Ch R = 1 ,1846.953,49.947400,49.947400,49.947400
XS GIS Cut Line= 6
1159698.11120588852311.8423182791159785.41366405852324.255128844
1159810.89961405852318.9759094621159841.73495803852297.428223393
1159860.56670229852291.3319075971159964.84914835852295.395890086
#Sta/Elev= 30
9861.644 263.9649873.682260.79729893.767 256.2529903.809253.13699923.685 247.709
9950.028241.90789953.284241.34289956.585240.43339973.481235.03059976.973234.2675
9984.483235.25649996.689235.591310001.01236.1259 10009.1237.512510020.16 239.752
10027.05241.403810040.53245.577310047.11248.073310056.99252.602310063.55256.4996
10070.11 260.84510073.39263.172210086.55274.334410093.14 279.52110099.74284.0494
10109.63290.041110116.22293.492510119.52294.845810129.41298.383510138.33301.0053
#Mann= 3 , 0 , 0
9861.644    0.12       09861.644    0.12       010138.33    0.12       0
#XS Ineff= 2 , 0
       0                               0
Bank Sta=9861.644,10138.33
Exp/Cntr=0.3,0.1

Type RM Length L Ch R = 1 ,1797.005,49.947400,49.947400,49.947400
XS GIS Cut Line= 6
 1159706.1906813852320.1706358511159748.01404996852330.081745576
1159825.65976464852343.7733025471159840.29915538 852349.21255645
1159842.14530924852349.9817871671159970.36554318852399.609623951
#Sta/Elev= 30
9861.558259.44719868.751257.42619882.238253.94199904.539246.85999915.819243.4756
9939.139238.24089952.465235.41599962.459232.6274 9965.79231.91059972.453230.8727
9979.116 230.156  9992.9229.04769999.914228.187810003.44229.057610010.48233.9952
10024.55244.234610031.72249.195710038.62253.663810045.66257.6153 10049.9259.5736
10056.21261.860810063.25264.638610084.36273.719710095.35 276.71810101.95279.1623
10108.98282.199310116.02 285.51610123.06289.074110133.61296.276610138.49 299.155
#Mann= 3 , 0 , 0
9861.558    0.12       09861.558    0.12       010138.49    0.12       0
#XS Ineff= 2 , 0
       0                               0
Bank Sta=9861.558,10138.49
Exp/Cntr=0.3,0.1

Type RM Length L Ch R = 1 ,1747.058,49.947500,49.947500,49.947500
XS GIS Cut Line= 6
1159685.98705844852326.9407997561159753.89395704852351.548261187
1159782.51707291852365.2517361921159797.01748119852375.664697621
1159841.52754201852414.9272912221159921.33277491852467.686205136
#Sta/Elev= 30
9861.568259.46299866.075 258.3719873.055256.47039893.992249.70169907.951 244.716
9921.909240.18729933.796 237.0539961.417229.3661 9965.53228.02399969.612226.5208
9989.905  218.489994.405217.43769995.614217.33539998.905217.993110000.31218.4497
10012.63222.958510014.53223.992210024.83 230.23510038.11238.0884 10042.8240.9418
10046.27243.1861 10050.2245.277410058.17248.680810070.07253.226510077.73256.5051
 10085.6260.199410101.33267.866510128.86280.848710132.79282.744310138.46 285.675
#Mann= 3 , 0 , 0
9861.568    0.12       09861.568    0.12       010138.46    0.12       0
#XS Ineff= 2 , 0
       0                               0
Bank Sta=9861.568,10138.46
Exp/Cntr=0.3,0.1

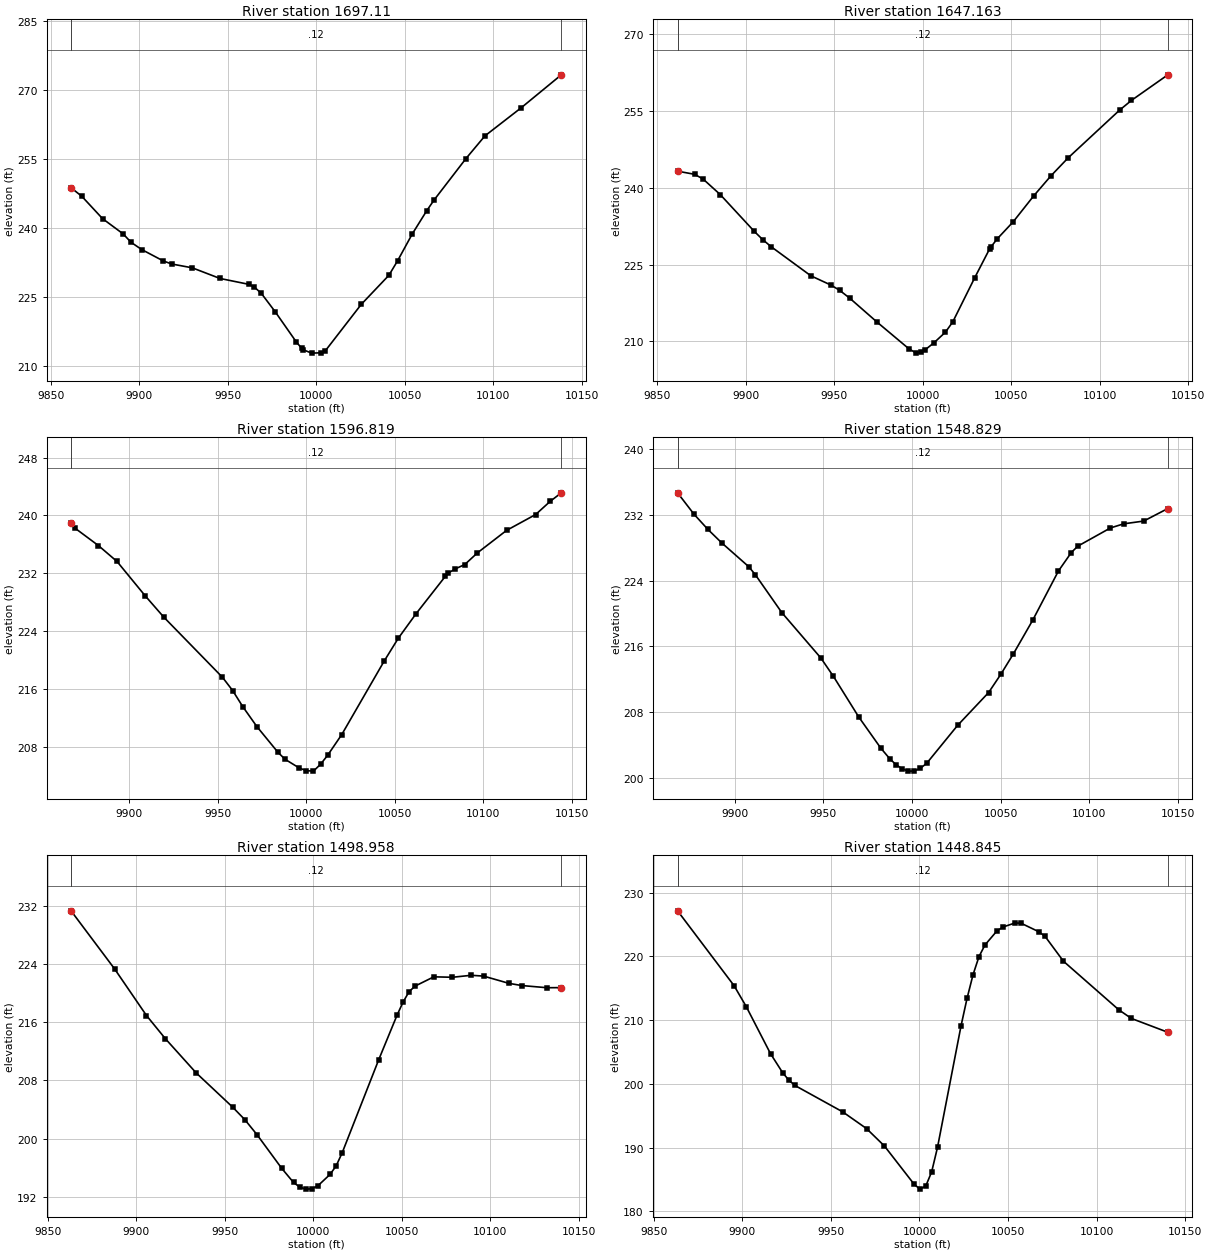
Type RM Length L Ch R = 1 , 1697.11,49.947400,49.947400,49.947400
XS GIS Cut Line= 5
1159665.43539631852352.5818599211159770.17787986852420.021768694
1159780.63857316852427.5918995391159782.24206492852428.787229691
1159891.98266704 852511.62670313
#Sta/Elev= 30
9861.512248.75569867.582246.89739879.289242.03069890.995238.68639895.374236.8771
9901.434235.29349913.555232.82269918.309 232.1489930.016231.30819945.624228.9955
9962.038227.70719965.134227.09799969.036225.7312 9976.84221.7434 9988.64215.2289
9991.861213.7379 9992.69213.45359997.457212.722510002.96212.796710004.92213.1038
10025.47223.346810041.08229.679510046.02232.856210054.25238.667710062.47243.7599
10066.58 246.07410084.64255.125310095.35260.0606 10115.9 266.204 10138.5273.3621
#Mann= 3 , 0 , 0
9861.512    0.12       09861.512    0.12       0 10138.5    0.12       0
#XS Ineff= 2 , 0
       0                               0
Bank Sta=9861.512,10138.5
Exp/Cntr=0.3,0.1

Type RM Length L Ch R = 1 ,1647.163,50.343800,50.343800,50.343800
XS GIS Cut Line= 6
1159648.18385352852377.4987491021159716.26157289852440.735839728
1159751.40414275 852468.119757711159753.04096884852469.269018508
1159781.37876828852491.1574811011159856.27196482 852559.91628301
#Sta/Elev= 30
9861.531243.24889871.138242.64399875.958 241.714  9885.6238.69559904.882231.4899
9909.703229.86169914.433228.49219936.823222.81869948.268220.99059953.089219.9834
9958.873218.42159974.294 213.7539992.147208.58129996.307207.7144    9999207.9068
10001.11 208.28610006.48209.767910012.83211.804110016.98213.806510029.41222.4527
10037.77228.0489 10038.5228.433710042.22230.078310051.13233.365910062.76238.4469
10072.46242.346410082.16245.851410111.27255.186610117.94257.079910138.48262.0703
#Mann= 3 , 0 , 0
9861.531    0.12       09861.531    0.12       010138.48    0.12       0
#XS Ineff= 2 , 0
       0                               0
Bank Sta=9861.531,10138.48
Exp/Cntr=0.3,0.1

Type RM Length L Ch R = 1 ,1596.819,47.989800,47.989800,47.989800
XS GIS Cut Line= 6
1159634.65642872852392.2838086881159675.62466576852443.629231681
1159716.57248136852502.5934934911159717.76701369852504.197579679
1159752.69962127852554.6499087331159798.54531723852615.419839176
#Sta/Elev= 30
9867.066238.91489869.107238.26159882.517235.81729893.037233.61379908.818228.8986
9919.339225.94129952.597217.58289958.348215.7518  9964.1213.51239972.041210.7602
9984.025207.17729988.019206.22699996.008205.0234   10000204.6563   10004204.5937
10008.04205.549810012.03206.790610020.01209.662710043.95219.825210051.93222.9886
 10061.9226.360610078.57231.577310080.22232.017210084.02  232.5810089.47233.1867
10096.66234.8122 10113.1237.918210129.54240.116710137.76241.941310144.03243.1177
#Mann= 3 , 0 , 0
9867.066    0.12       09867.066    0.12       010144.03    0.12       0
#XS Ineff= 2 , 0
       0                               0
Bank Sta=9867.066,10144.03
Exp/Cntr=0.3,0.1

Type RM Length L Ch R = 1 ,1548.829,49.871400,49.871400,49.871400
XS GIS Cut Line= 6
1159610.90030171852399.2544429511159628.63547799 852426.34370928
1159647.67539897852461.3315984241159661.42193824852493.311052197
1159690.11998114852572.2560615771159729.45570062852648.576050993
#Sta/Elev= 30
9867.575234.70439876.836 232.1079884.678230.25769892.521228.60819907.815225.7017
 9911.55224.71519926.491 220.1079948.501214.58989955.644212.33789969.928207.3965
9982.417203.59489987.415202.31739990.887201.60659994.358 201.096 9997.83200.8039
 10001.3200.813710004.77201.161810008.23201.740210025.76206.376410043.29210.3802
 10050.3212.641210057.31215.103910068.17219.183310082.72225.184510089.99227.4303
10093.63228.2056 10112.1230.427610119.61230.929310130.87231.262710144.51232.7907
#Mann= 3 , 0 , 0
9867.575    0.12       09867.575    0.12       010144.51    0.12       0
#XS Ineff= 2 , 0
       0                               0
Bank Sta=9867.575,10144.51
Exp/Cntr=0.3,0.1

Type RM Length L Ch R = 1 ,1498.958,50.112900,50.112900,50.112900
XS GIS Cut Line= 6
1159575.41265666852407.9520733331159589.86718729852436.922781452
1159599.87217068852461.0693778331159641.43920355 852593.21513258
1159656.12485136852631.5128943681159672.10860855852666.952048162
#Sta/Elev= 30
9863.202231.38099887.806223.37239905.807216.95219916.461213.76099933.825209.0561
9954.464204.32819961.344202.60219968.223200.53469982.193195.89149988.862193.9397
9992.302193.31899995.742193.02289999.182193.065510002.61 193.47810009.49195.0504
10012.93196.218510016.37198.0401   10037210.865910047.32216.981310050.76  218.81
 10054.2220.259710057.64221.020610068.12222.284910078.66222.223110089.21 222.495
10096.23222.385310110.51221.386810117.71221.0849 10132.1220.781310140.14220.7975
#Mann= 3 , 0 , 0
9863.202    0.12       09863.202    0.12       010140.14    0.12       0
#XS Ineff= 2 , 0
       0                               0
Bank Sta=9863.202,10140.14
Exp/Cntr=0.3,0.1

Type RM Length L Ch R = 1 ,1448.845,49.755600,49.755600,49.755600
XS GIS Cut Line= 6
1159539.32889894852420.0021217121159551.31196399852450.079399165
1159562.94857486852488.1782185851159589.63645609852611.756003803
1159600.58739112852646.1896838731159615.95342354852685.361274278
#Sta/Elev= 30
9863.351227.16279895.269215.41799902.143212.13469915.865204.74389922.726201.7575
9926.156200.60899929.586199.76749956.641 195.6169970.115192.9891 9980.22190.2565
9996.913 184.28410000.23183.493810003.54183.970410006.87186.1892 10010.2190.0671
10023.51209.158110026.86213.411410030.24 217.12410033.63219.988710037.01221.8085
10043.78 224.01610047.16224.619910053.93225.254310057.31 225.22810067.55 223.863
   10071223.134510081.32219.256210112.64 211.62210119.69 210.27710140.29208.1069
#Mann= 3 , 0 , 0
9863.351    0.12       09863.351    0.12       010140.29    0.12       0
#XS Ineff= 2 , 0
       0                               0
Bank Sta=9863.351,10140.29
Exp/Cntr=0.3,0.1

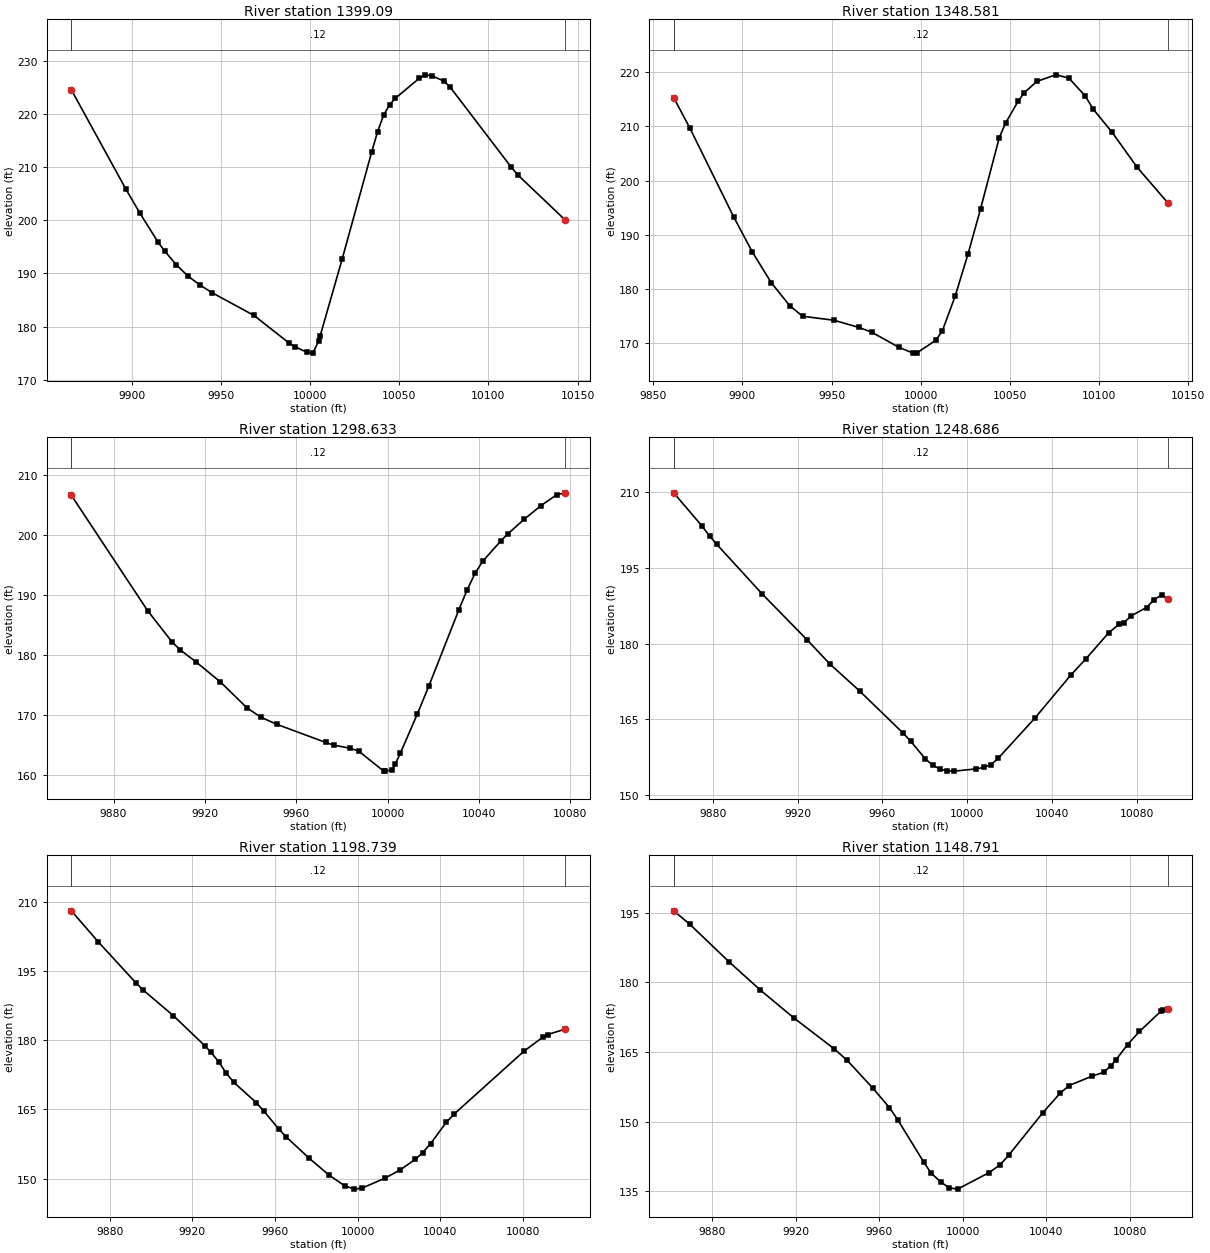
Type RM Length L Ch R = 1 , 1399.09,50.508600,50.508600,50.508600
XS GIS Cut Line= 6
1159495.98985913852423.579573728 1159510.4331003852462.938482623
1159520.89187735852503.2032844791159528.77939405852581.519857735
 1159534.4415936852612.0475410491159560.76839374852691.267986989
#Sta/Elev= 30
9866.209 224.5959896.711205.91799904.467201.45549914.746195.92479918.582 194.198
9924.915 191.6749931.695189.47629938.474187.77429945.254186.34679968.587182.0905
9988.432176.84799991.719176.17529998.294175.147710001.58174.993410004.87177.3234
10005.66178.215110018.02192.713210034.55212.865610037.89216.724210041.23 219.801
10044.56221.7657 10047.9223.020810061.29226.7762 10064.7227.420410068.12227.2575
10074.95226.259810078.37225.180710112.84210.006310116.34208.613310143.11200.0459
#Mann= 3 , 0 , 0
9866.209    0.12       09866.209    0.12       010143.11    0.12       0
#XS Ineff= 2 , 0
       0                               0
Bank Sta=9866.209,10143.11
Exp/Cntr=0.3,0.1

Type RM Length L Ch R = 1 ,1348.581,49.947400,49.947400,49.947400
XS GIS Cut Line= 6
1159427.23257334 852438.061903521159466.93092628852540.440013804
1159478.33158499852565.656846092 1159479.2100053852567.453614788
1159490.46993688852592.7307654031159529.50060899852695.364486019
#Sta/Elev= 30
 9861.52215.30499870.434209.78969895.066193.35799905.622186.83119916.179181.1893
9926.497176.96199933.773174.98369951.367174.24859965.443172.91429972.507172.0468
9987.732169.26749995.696168.18329997.711168.191510008.52170.568510012.11172.2629
 10019.3 178.66610026.48186.398710033.55194.769510044.08207.939110047.59210.6162
10054.61214.630210058.12216.237310065.14218.294210075.67219.513110082.99218.9403
10092.22215.639610096.73213.182310107.26 208.942 10121.3202.482710138.48195.9339
#Mann= 3 , 0 , 0
 9861.52    0.12       0 9861.52    0.12       010138.48    0.12       0
#XS Ineff= 2 , 0
       0                               0
Bank Sta=9861.52,10138.48
Exp/Cntr=0.3,0.1

Type RM Length L Ch R = 1 ,1298.633,49.947500,49.947500,49.947500
XS GIS Cut Line= 6
1159382.37837683852464.6434977851159425.56589633852570.811940265
1159435.51031844852591.4011530661159436.52992327852593.121736104
 1159447.6750278852615.500485943 1159468.6277085852662.948834187
#Sta/Elev= 30
9861.519206.60169894.922187.41389905.548182.2386 9909.09180.91089916.174 178.865
9926.799 175.5499938.417171.24329944.509169.67959951.592168.48769972.844165.4889
9976.393165.0431 9983.68164.50869987.323164.04729998.254160.7337    9999160.7082
10001.99160.8971 10003.4161.890810005.66163.731110012.99170.161710018.12174.8841
 10031.2187.510810034.79 190.80910038.37193.647810041.67195.624710049.79199.0835
10052.72200.193410059.89202.634210067.06204.847110074.16206.719610077.87207.0206
#Mann= 3 , 0 , 0
9861.519    0.12       09861.519    0.12       010077.87    0.12       0
#XS Ineff= 2 , 0
       0                               0
Bank Sta=9861.519,10077.87
Exp/Cntr=0.3,0.1

Type RM Length L Ch R = 1 ,1248.686,49.947400,49.947400,49.947400
XS GIS Cut Line= 6
 1159339.2351609852473.516098285 1159371.3933992852550.853948099
1159387.71677166852602.0151188011159388.44557041852603.877604341
1159404.56804989852655.3152117691159420.53750541852691.694481904
#Sta/Elev= 30
9861.541209.87859874.782203.35789878.475201.31919881.888199.66249903.207189.8868
9924.526 180.7439935.186175.99759949.272170.63519969.935162.23569973.378160.6805
9980.266157.1938 9983.71155.95069987.154155.17169990.597154.82039994.041 154.764
10004.41155.213710007.85155.496310011.29156.051810014.73157.331510031.92165.2382
10049.11173.871610056.03176.988610066.78 182.14910071.79183.870510073.95184.1682
10077.53185.541310084.69187.166510088.28188.750610091.86189.647610094.64188.8016
#Mann= 3 , 0 , 0
9861.541    0.12       09861.541    0.12       010094.64    0.12       0
#XS Ineff= 2 , 0
       0                               0
Bank Sta=9861.541,10094.64
Exp/Cntr=0.3,0.1

Type RM Length L Ch R = 1 ,1198.739,49.947400,49.947400,49.947400
XS GIS Cut Line= 5
1159281.54703268852497.081211313 1159341.5043845852620.809430713
 1159342.4525842852622.5703728861159356.29058317852649.691399016
 1159390.3818859852709.719833424
#Sta/Elev= 30
 9861.51207.9963 9874.43201.32289892.659192.42749896.305190.81759910.902185.2696
9925.949178.81839929.116177.30939932.762175.31189936.408172.85219940.054170.8532
9950.991 166.4299954.637164.62459961.928160.67869965.574158.97079976.511154.4153
9986.136150.7617 9993.66148.44659998.386147.707810002.09147.920310013.14 150.062
 10020.5151.849710027.87154.146510031.55155.638510035.33157.573710042.87162.1668
10046.65163.9543 10080.6177.6349 10089.8180.689710091.92181.193310100.48182.3729
#Mann= 3 , 0 , 0
 9861.51    0.12       0 9861.51    0.12       010100.48    0.12       0
#XS Ineff= 2 , 0
       0                               0
Bank Sta=9861.51,10100.48
Exp/Cntr=0.3,0.1

Type RM Length L Ch R = 1 ,1148.791,49.947500,49.947500,49.947500
XS GIS Cut Line= 6
1159228.30617273852531.6377913811159256.60578371852581.693485061
1159278.35589734852616.1976211751159302.80293089 852649.34597124
 1159341.7352094852701.6797428991159360.04209343852727.855273287
#Sta/Elev= 30
 9861.52195.3911  9869.1192.55459887.944184.4472 9903.02178.33899919.022172.3603
9938.509 165.6519944.661163.19549956.851157.26249964.862153.04629968.946150.3434
9981.197141.39019984.811138.95149989.365137.06019993.449135.79319997.533135.4947
10012.47 139.012 10017.9140.737510021.99142.782510038.35151.938310046.53156.0819
10050.94157.789310061.94159.807510067.49 160.62910070.96162.065410073.21163.2222
10078.93166.579910084.66169.431510094.98173.791310096.11174.089110098.17174.1788
#Mann= 3 , 0 , 0
 9861.52    0.12       0 9861.52    0.12       010098.17    0.12       0
#XS Ineff= 2 , 0
       0                               0
Bank Sta=9861.52,10098.17
Exp/Cntr=0.3,0.1

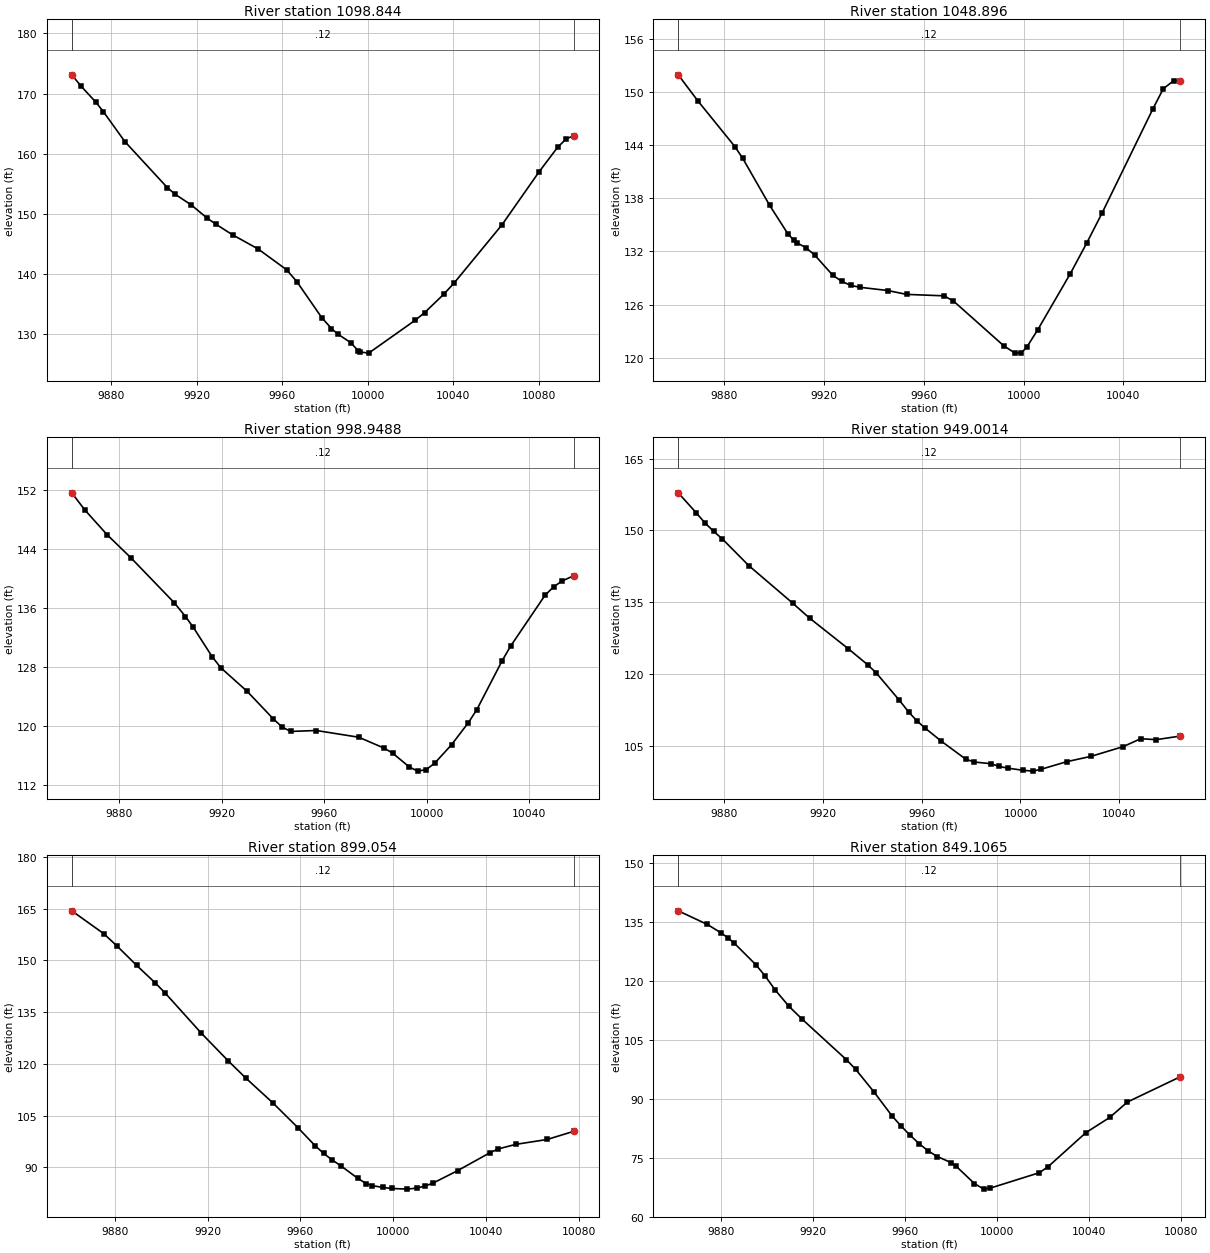
Type RM Length L Ch R = 1 ,1098.844,49.947400,49.947400,49.947400
XS GIS Cut Line= 6
1159182.87756875852561.4116992831159213.31650411852616.991262003
1159233.47084526852646.8955958631159261.08042569852676.442712687
1159301.43260171852714.0548023551159327.08633801852744.389526615
#Sta/Elev= 30
9861.574173.10939865.943 171.2199872.773168.58759876.297167.01129886.433162.0004
9906.222154.37999909.962153.24489917.444151.48819924.925149.2808 9928.88148.3047
9936.793146.51189948.662144.17899962.049140.70929966.823138.74529978.532 132.731
9983.048130.94039985.916130.03249992.082128.58639995.463127.28129996.599  127.04
10000.45126.850910022.23132.324210026.56133.572310035.45136.597410040.39138.5011
10062.79148.179110080.15156.992210088.77161.042210092.93162.5021 10096.4 162.971
#Mann= 3 , 0 , 0
9861.574    0.12       09861.574    0.12       0 10096.4    0.12       0
#XS Ineff= 2 , 0
       0                               0
Bank Sta=9861.574,10096.4
Exp/Cntr=0.3,0.1

Type RM Length L Ch R = 1 ,1048.896,49.947500,49.947500,49.947500
XS GIS Cut Line= 6
1159168.95545357852596.7423428781159199.88104607852664.250451294
1159218.56477039852697.3996054051159229.52709262852712.337111264
1159251.53687918852736.7563297231159274.15542101852766.774407811
#Sta/Elev= 30
9861.546151.93549869.367 149.0119884.258143.8346 9887.41142.50249898.236137.1833
9905.454134.01189907.891133.25429909.063132.97979912.671  132.44 9916.28131.5839
9923.497129.31239927.106128.61999930.715128.16489934.323127.95229945.536127.5846
9953.089127.14849968.154126.9839 9971.92126.39599992.112121.33449996.592120.5164
9999.157 120.56110001.34 121.20610005.68123.143910018.72129.465310025.28132.9095
10031.41136.282410051.95148.132510056.05150.367610060.16151.261910062.87 151.275
#Mann= 3 , 0 , 0
9861.546    0.12       09861.546    0.12       010062.87    0.12       0
#XS Ineff= 2 , 0
       0                               0
Bank Sta=9861.546,10062.87
Exp/Cntr=0.3,0.1

Type RM Length L Ch R = 1 ,998.9488,49.947400,49.947400,49.947400
XS GIS Cut Line= 6
1159153.54275639852595.543797463 1159171.3668748852639.513531821
1159181.54136713852674.2406938081159185.61348545852700.054789346
1159189.60805931852760.0425501751159194.83122429852785.505205539
#Sta/Elev= 30
9861.556 151.605 9866.63149.29539875.363  145.939884.682142.79529901.562136.7218
9905.923134.86069909.001133.38959916.285129.45019919.704127.9307 9929.96124.7483
9940.216121.00529943.635119.90439947.001119.31539956.965 119.4419973.548118.5295
9983.407117.05749986.694116.39099993.267 114.5019996.553113.9438 9999.84114.1532
10003.13115.009910009.71117.509410016.29120.501110019.58122.259910029.45128.8738
10032.76130.854910046.16137.720510049.51138.877610052.86139.670910057.44140.3966
#Mann= 3 , 0 , 0
9861.556    0.12       09861.556    0.12       010057.44    0.12       0
#XS Ineff= 2 , 0
       0                               0
Bank Sta=9861.556,10057.44
Exp/Cntr=0.3,0.1

Type RM Length L Ch R = 1 ,949.0014,49.947400,49.947400,49.947400
XS GIS Cut Line= 6
1159118.81857702852587.3293063331159137.12969378 852632.18961529
1159145.44936317852672.2374578891159144.05089942 852701.22792993
1159131.15001225852747.974388891  1159135.718407852783.244059526
#Sta/Elev= 30
9861.665157.84639868.881153.71319872.425151.59049875.969149.82659879.512148.2274
9890.143142.69369907.861134.87989914.749131.72969930.455125.3257 9938.34121.9645
9941.657120.3274 9951.09114.57669954.888112.10289958.172110.30049961.457108.8021
9968.026106.0715 9977.88102.32979981.205101.74549988.024101.38799991.434100.8105
9994.844100.4657   10001100.012110005.0999.8391210008.48100.251810018.67101.8027
10028.61102.933710041.45104.936410048.61106.595510054.84106.3964 10064.6107.1481
#Mann= 3 , 0 , 0
9861.665    0.12       09861.665    0.12       0 10064.6    0.12       0
#XS Ineff= 2 , 0
       0                               0
Bank Sta=9861.665,10064.6
Exp/Cntr=0.3,0.1

Type RM Length L Ch R = 1 , 899.054,49.947500,49.947500,49.947500
XS GIS Cut Line= 6
1159019.42631258852600.9696767631159046.79634647852638.531956928
1159066.60019554852670.9091153211159092.29043917852722.733708858
1159107.60554952852761.5839331211159124.71147493852788.708048368
#Sta/Elev= 30
9861.536164.3859 9875.24157.79249880.811154.32789889.459  148.589897.578143.4285
9901.638140.63829917.357128.89049928.894120.89229936.586115.83589948.019108.7761
9958.996101.46489966.31596.294229969.97494.081579973.63392.164269977.292 90.5221
 9984.6186.873939988.26985.323469991.02284.698519995.58884.181279999.25283.88594
10006.0583.6959210010.0383.9925210013.5684.5716810017.0985.4359110027.6789.03627
10041.7794.30824 10045.395.3664510052.7696.6762610066.2498.0876110077.76100.4664
#Mann= 3 , 0 , 0
9861.536    0.12       09861.536    0.12       010077.76    0.12       0
#XS Ineff= 2 , 0
       0                               0
Bank Sta=9861.536,10077.76
Exp/Cntr=0.3,0.1

Type RM Length L Ch R = 1 ,849.1065,49.947400,49.947400,49.947400
XS GIS Cut Line= 6
1158937.16128611852672.281694468 1159030.4010017852734.619037084
1159050.95097111852749.4410287471159065.22450242 852759.77421464
 1159107.7714417852785.3089709581159118.13140744852794.040172034
#Sta/Elev= 30
9861.504137.82279874.152134.36459880.055132.24029883.345130.85999885.958129.5415
9895.184124.16359899.131  121.379903.667117.6893 9909.57113.59289915.473110.2215
 9934.6599.959929938.59697.560979946.48991.865339954.38285.740289958.32983.14323
9962.27580.797229966.222 78.63719970.16876.782289974.12675.360849980.06973.82726
9982.21772.950999990.30768.473879994.35267.071259996.89467.2790310018.5471.25236
10022.3672.7985310038.7881.4470510049.1585.31186 10056.889.2196810079.79 95.6371
#Mann= 3 , 0 , 0
9861.504    0.12       09861.504    0.12       010079.79    0.12       0
#XS Ineff= 2 , 0
       0                               0
Bank Sta=9861.504,10079.79
Exp/Cntr=0.3,0.1