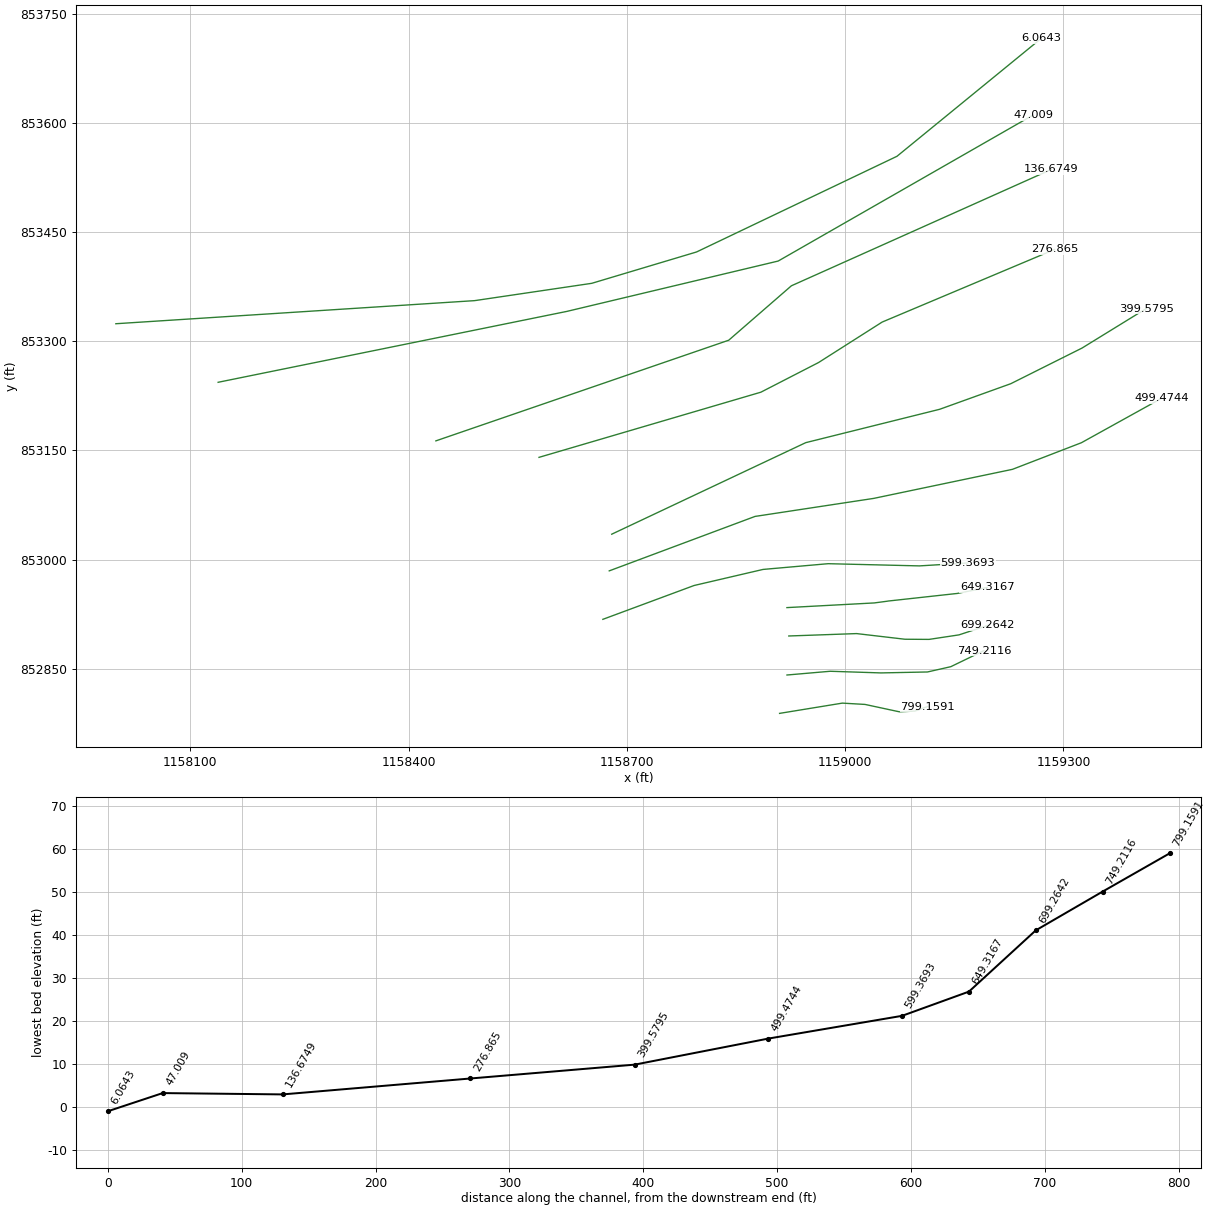
HEC-RAS study 184_ras.prj: 184

--- 184_ras.g01 (geometry) --- (continued)

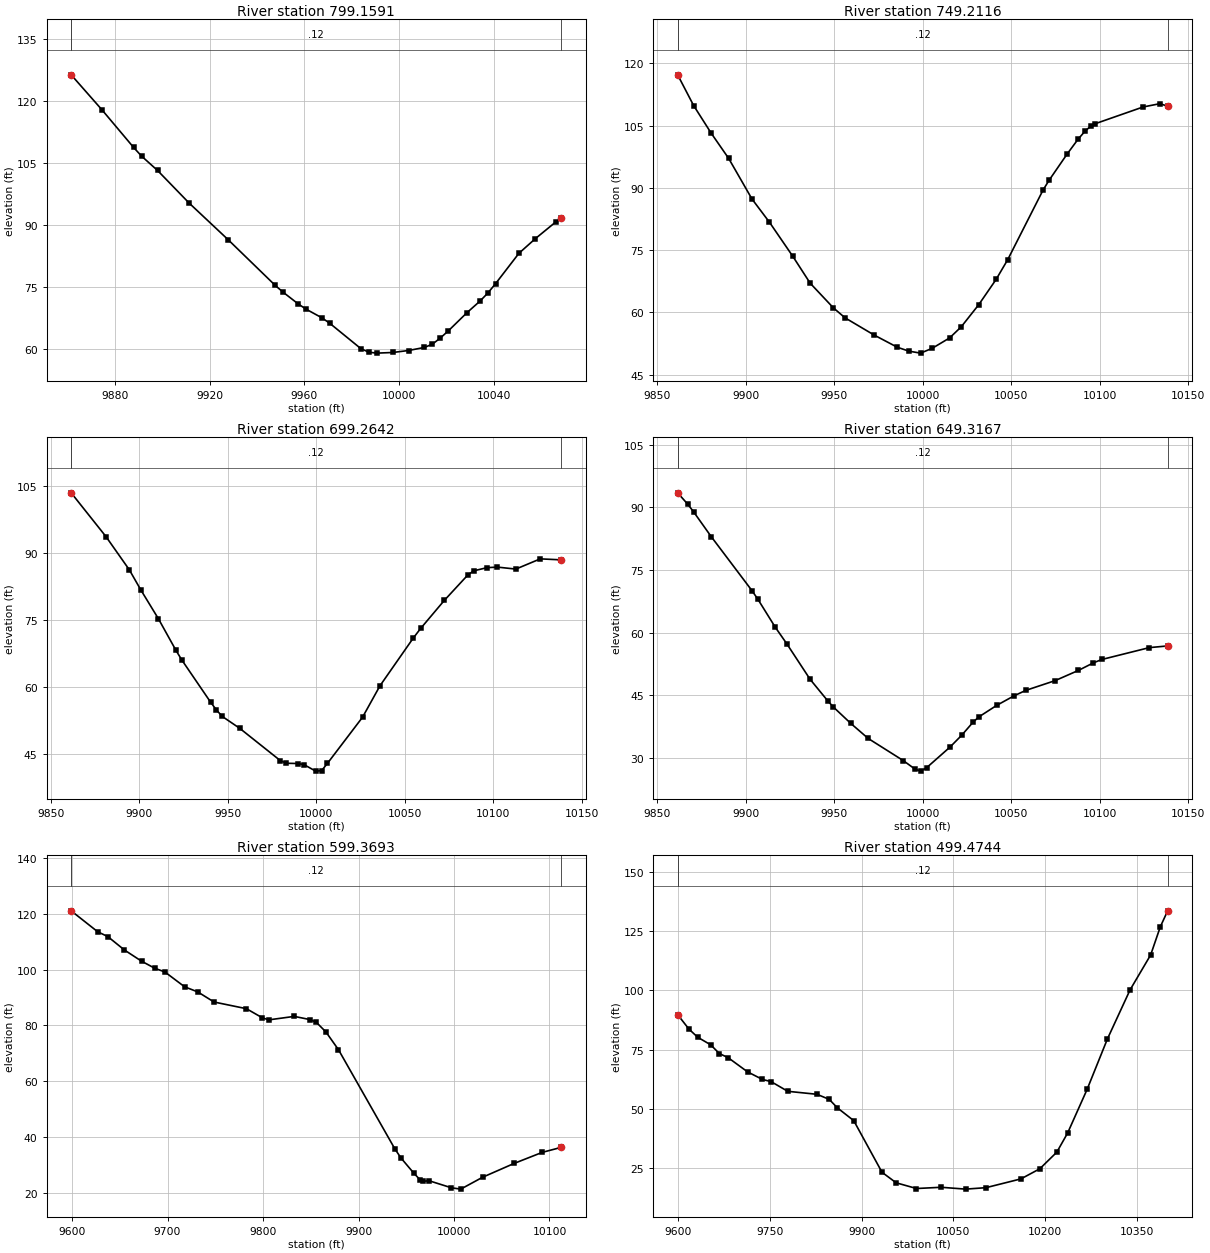
Type RM Length L Ch R = 1 ,799.1591,49.947500,49.947500,49.947500
XS GIS Cut Line= 6
1158909.88814383852788.7091230991158996.09960754852802.804418299
  1159027.338185852800.9997326341159074.52030301852790.847736935
1159095.76689554852791.8595795431159113.15168943852798.075460764
#Sta/Elev= 30
9861.597126.30899874.522117.8999 9887.96108.7493 9891.32106.65419898.039103.1973
9911.398 95.30219927.88886.433729947.67775.432249950.969 73.79789957.54170.87787
9960.828 69.6352  9967.4   67.589970.68666.273049983.89660.109049987.24359.26232
 9990.5959.034459997.28559.18646   1000459.6689510010.7260.4176210014.0861.20805
10017.4562.7082810020.81 64.429810028.6568.8117410034.1371.5973910037.4173.53033
 10040.7 75.807610050.5883.16384 10057.586.6996510066.1290.7372610068.4291.65653
#Mann= 3 , 0 , 0
9861.597    0.12       09861.597    0.12       010068.42    0.12       0
#XS Ineff= 2 , 0
       0                               0
Bank Sta=9861.597,10068.42
Exp/Cntr=0.3,0.1

Type RM Length L Ch R = 1 ,749.2116,49.947400,49.947400,49.947400
XS GIS Cut Line= 6
1158920.04914591852841.4343398941158979.44490089852846.582411008
1159049.21183183852844.3082275381159113.12846112852845.606666127
1159145.17682479852852.8742722331159190.68272495852874.895794939
#Sta/Elev= 30
 9861.56117.21199870.616109.79169880.495103.15819890.37497.077449903.54787.29197
9913.42681.690539926.58273.500079936.429 67.0019 9949.5661.050649956.12558.65799
9972.53854.514939985.668 51.56459992.23250.624699998.79450.1512610005.3651.30927
 10015.253.8158910021.7756.4921610031.6161.7981210041.4667.9074410048.0272.66907
10068.0389.48244 10071.491.8070910081.4998.0672210087.78101.704110091.79103.6761
10095.33104.987710097.32105.411510124.51109.464710134.08110.265310138.39109.6326
#Mann= 3 , 0 , 0
 9861.56    0.12       0 9861.56    0.12       010138.39    0.12       0
#XS Ineff= 2 , 0
       0                               0
Bank Sta=9861.56,10138.39
Exp/Cntr=0.3,0.1

Type RM Length L Ch R = 1 ,699.2642,49.947500,49.947500,49.947500
XS GIS Cut Line= 6
 1158922.5509522852895.0660661171159015.69222782852898.359601919
1159082.16674914852890.587506076 1159115.2823434852890.387749286
1159156.38498886852896.5796409411159196.20793956852909.621155934
#Sta/Elev= 30
9861.531103.41099881.21893.601399894.37186.189769900.94781.637949910.80775.23113
 9920.6568.210599923.93166.063549940.33556.534799943.61654.796669946.89753.36169
9956.74350.707989979.75343.45896 9983.0442.883629989.68742.822499993.01242.58861
9999.66841.12085   1000341.2232610006.3242.8608710026.1753.2002910036.0160.23357
 10054.9 70.960210059.0273.0782510072.2979.3121510085.5684.9946310088.8885.94468
10096.4686.6643910102.3886.7833710112.7486.3430210126.5588.6302110138.3788.40903
#Mann= 3 , 0 , 0
9861.531    0.12       09861.531    0.12       010138.37    0.12       0
#XS Ineff= 2 , 0
       0                               0
Bank Sta=9861.531,10138.37
Exp/Cntr=0.3,0.1

Type RM Length L Ch R = 1 ,649.3167,49.947400,49.947400,49.947400
XS GIS Cut Line= 6
1158919.96698667852934.0622171461159040.08018491852940.496884323
1159057.11502487  852942.75408121159059.08781273852943.082879119
1159154.05066529852953.523335804 1159195.1636546852961.716088884
#Sta/Elev= 30
9861.53193.476779867.36390.688049870.64888.868059880.50582.987439903.50470.07572
9906.78968.056139916.64661.337859923.21757.339149936.359 48.84929946.21643.75276
9949.50142.212519959.35838.285969969.214 34.67769988.97929.392629995.59927.36398
9998.90826.8562810002.2227.6672110015.4332.6060310022.0335.4334210028.6338.64281
10031.9339.8849910041.83 42.595310051.7344.9019110058.3346.1944310074.8448.51722
10088.0450.9705610096.5452.7888210101.31 53.588910128.0756.4201610138.4656.82569
#Mann= 3 , 0 , 0
9861.531    0.12       09861.531    0.12       010138.46    0.12       0
#XS Ineff= 2 , 0
       0                               0
Bank Sta=9861.531,10138.46
Exp/Cntr=0.3,0.1

Type RM Length L Ch R = 1 ,599.3693,99.894900,99.894900,99.894900
XS GIS Cut Line= 6
1158667.01301373852917.9564270181158792.39549154852964.453647967
1158887.14539495852986.5333929161158976.59568417852994.421089268
1159102.09797411852991.3942115221159168.59024845852995.427707225
#Sta/Elev= 30
9599.064121.10929626.856113.59239637.443111.86179654.828107.05179672.733103.0429
9686.749 100.4749697.11499.191489717.845 93.84539731.665 91.99959748.68588.37724
9782.58985.981249799.32482.702869806.01881.972569832.76283.217169849.29682.05966
 9855.9181.055049865.83177.653239879.01271.255559938.13435.615199944.69732.29172
9957.82426.981749964.38724.586899967.66824.073499974.23124.188159997.20221.70265
10007.0521.2151710030.0225.4910310062.8430.4246410092.4434.4155310112.2536.19972
#Mann= 3 , 0 , 0
9599.064    0.12       09599.064    0.12       010112.25    0.12       0
#XS Ineff= 2 , 0
       0                               0
Bank Sta=9599.064,10112.25
Exp/Cntr=0.3,0.1

Type RM Length L Ch R = 1 ,499.4744,99.894900,99.894900,99.894900
XS GIS Cut Line= 6
1158675.79411273852984.5705297751158876.14452698853059.384539824
1159039.16212785853084.1415571381159229.93244099853124.101266501
 1159324.7083242853160.6773868921159434.81790054853221.675247233
#Sta/Elev= 30
9599.10389.745559617.58683.635789631.80680.206449653.13676.985839667.35673.28319
9681.57671.563919713.481 65.54389737.89662.322439751.84761.424019779.32957.30863
9827.00656.049289847.10853.905549860.50950.306169887.25544.893749933.47223.05666
9956.58118.604369989.88116.1782710030.3816.7023610070.29 15.919810103.5416.53326
10160.7920.2502710191.7224.5349210219.5131.5609210237.1239.6198410269.0358.09342
10302.2679.4356810339.39100.232910373.07 115.01810388.91126.951210400.91133.6768
#Mann= 3 , 0 , 0
9599.103    0.12       09599.103    0.12       010400.91    0.12       0
#XS Ineff= 2 , 0
       0                               0
Bank Sta=9599.103,10400.91
Exp/Cntr=0.3,0.1

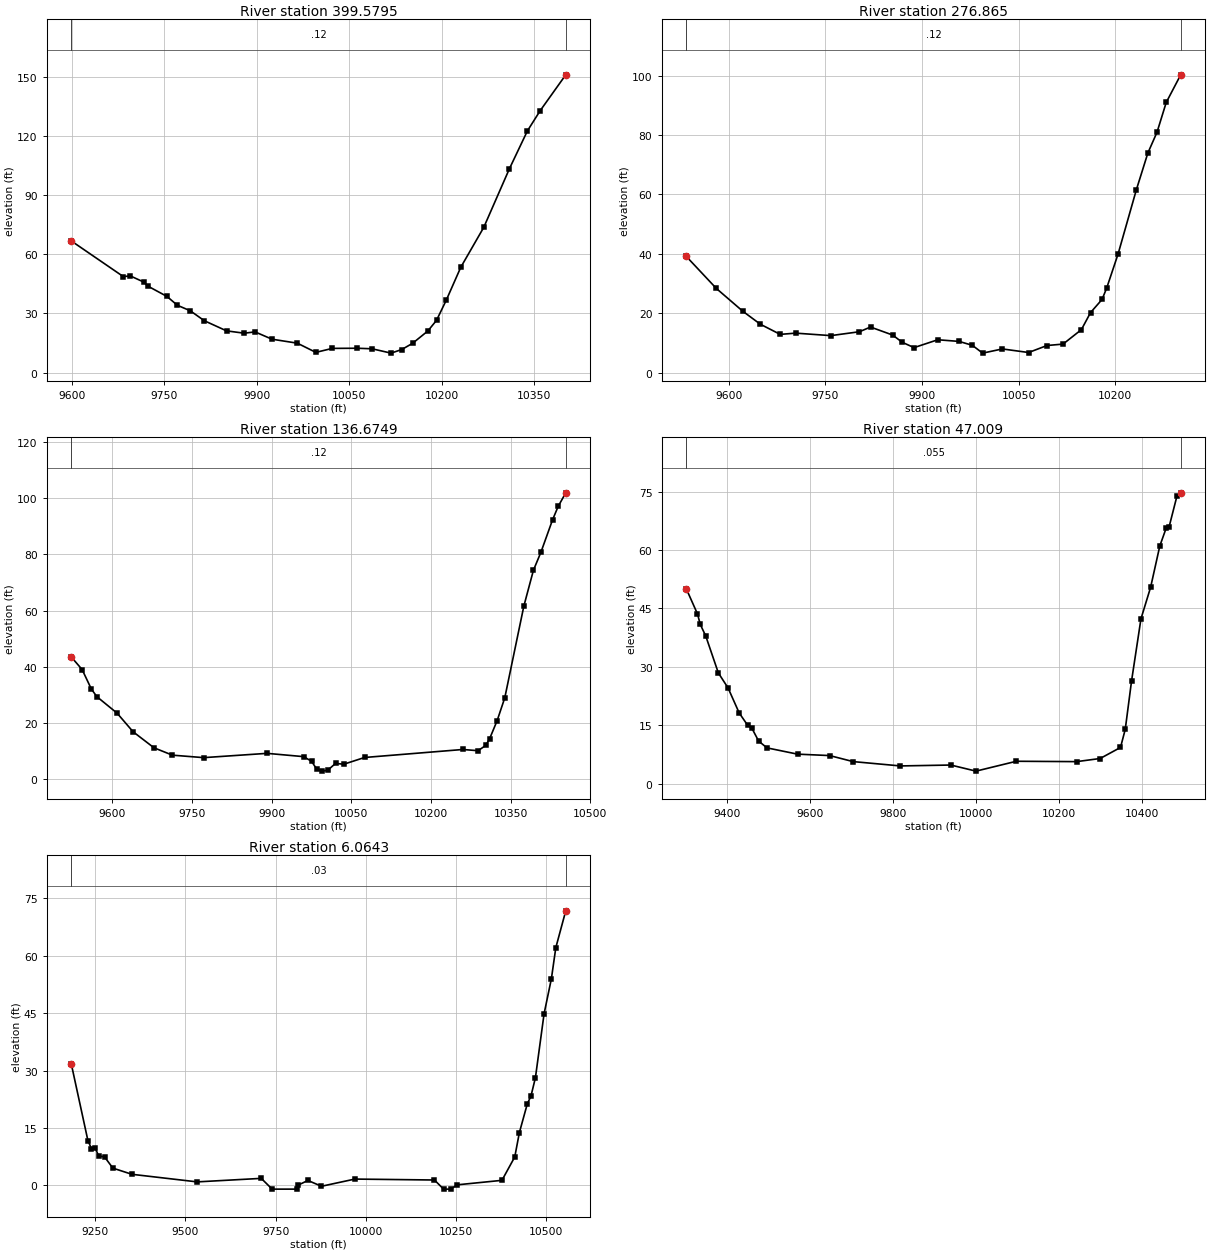
Type RM Length L Ch R = 1 ,399.5795,122.714500,122.714500,122.714500
XS GIS Cut Line= 6
1158679.20646827853034.9553770141158945.83257861853160.759454027
1159129.80595089853206.5971834881159227.64164801853241.794172404
1159325.48585704853290.7329713031159413.81738351853345.100060077
#Sta/Elev= 30
9599.07366.817959683.48848.706059694.42349.127389716.29345.980189723.583 43.8206
9754.18938.641199770.96834.163029791.83931.380129814.708 26.31389850.71621.16345
9879.40919.974329897.00120.641789924.46716.921269965.48614.913869995.60710.23301
10022.2912.25728 10062.812.3312510086.7912.0528110117.579.84903810134.8911.67069
10152.5114.8425210177.1821.0815810191.3826.5311210207.4837.0047710230.6153.44172
10268.0773.8341510309.43 103.46710338.76122.790110359.52133.078210400.93151.2651
#Mann= 3 , 0 , 0
9599.073    0.12       09599.073    0.12       010400.93    0.12       0
#XS Ineff= 2 , 0
       09873.723                       0
Bank Sta=9599.073,10400.93
Exp/Cntr=0.3,0.1

Type RM Length L Ch R = 1 , 276.865,140.190100,140.190100,140.190100
XS GIS Cut Line= 5
1158579.24514604853140.5620090811158884.17574465853230.114117995
1158963.52571458853270.9226739261159050.81068146853326.467652872
1159287.72702017853426.221900746
#Sta/Elev= 30
9534.22439.143819580.82128.383949621.85320.725649649.20816.337929679.98312.93178
9703.91913.349759758.62912.514819803.08113.825359820.17815.404359854.55712.70957
9869.31410.28553 9887.768.4777899924.59411.119479957.61810.569859978.1989.266477
9994.2836.62500210024.86 8.03269 10065.76.83288810094.189.186315 10119.19.660438
10147.58  14.52110161.8220.2690910179.6124.6697810186.73 28.423710204.5339.95147
10233.0161.6333510250.8173.9537810265.0580.96448 10279.390.9560610301.78100.2513
#Mann= 3 , 0 , 0
9534.224    0.12       09534.224    0.12       010301.78    0.12       0
#XS Ineff= 2 , 0
       09846.489                       0
Bank Sta=9534.224,10301.78
Exp/Cntr=0.3,0.1

Type RM Length L Ch R = 1 ,136.6749,89.665900,89.665900,89.665900
XS GIS Cut Line= 4
1158437.54877117853163.233429059 1158839.9664757853301.529090911
1158926.11787158853376.3447768241159283.19273615853536.178287625
#Sta/Elev= 30
9523.05543.467199543.23339.056929560.57932.141589570.98629.408419609.14723.52927
9639.14816.93299 9678.5311.224779713.2228.5996369772.1987.7147179891.5159.240236
 9960.328.0718849975.3376.4143469985.3393.5064499995.3462.91975910005.753.246384
10020.365.64988110036.175.39075510075.077.77104710260.02 10.613210288.7710.18513
10303.1512.0474310310.3414.3540310324.7220.88694 10339.129.0068710375.0461.64847
10393.0174.3462710407.3980.8929710428.9692.2564910439.7497.1147510453.89101.8923
#Mann= 3 , 0 , 0
9523.055    0.12       09523.055    0.12       010453.89    0.12       0
#XS Ineff= 2 , 0
       09928.427        10126.67       0
Bank Sta=9523.055,10453.89
Exp/Cntr=0.3,0.1

Type RM Length L Ch R = 1 ,  47.009,40.944700,40.944700,40.944700
XS GIS Cut Line= 4
1158138.28602752853243.7169699821158617.78655994853341.204075843
 1158907.9807356853410.351906776 1159258.2541742853610.993973538
#Sta/Elev= 30
9302.08950.019529328.97943.582699335.675 40.90379349.06737.868089379.19828.45326
9402.63424.586069429.41818.174949449.50615.051169459.54914.347429476.289 10.9494
9496.3779.2003059570.0327.587702 9647.397.222377 9703.955.6760549817.9754.560789
9939.3924.791829 10000.13.227358 10097.55.75954610242.58 5.6651410299.296.468963
10348.329.30527910359.7913.9594810374.9126.34316 10397.642.3117610420.9350.44706
10442.9761.0103510458.0965.5466210465.65 66.027710484.5673.9436410493.3974.68568
#Mann= 3 , 0 , 0
9302.089   0.055       09302.089   0.055       010493.39   0.055       0
#XS Ineff= 2 , 0
       09933.614        10157.82       0
Bank Sta=9302.089,10493.39
Exp/Cntr=0.3,0.1

Type RM Length L Ch R = 1 ,  6.0643,0.000000,0.000000,0.000000
XS GIS Cut Line= 6
1157997.72322369853324.2005108591158490.82660812853355.940498829
1158651.79368991853379.7454898211158795.75720674853422.821187764
1159071.21495944853554.3154236081159269.58988419853716.416076422
#Sta/Elev= 30
9183.81331.602269229.58811.704249239.4849.5823659249.3819.8626549259.2787.684414
9275.7737.4145639298.8664.4876349351.6492.8758589532.5210.8938299710.0791.812157
9740.281  -0.9999809.574  -0.9999812.8910.0714599839.4231.265599 9877.04-0.25216
9969.5031.62904810190.15 1.3845210215.51  -0.99910234.78  -0.99910254.04 0.13295
10377.261.29767610412.787.41374410425.5313.7643810447.7921.3693110457.4723.24782
10470.0428.1209710494.0344.8320810514.3454.0062610526.5262.0912810554.1171.73226
#Mann= 3 , 0 , 0
9183.813    0.03       09183.813    0.03       010554.11    0.03       0
#XS Ineff= 2 , 0
       09926.969        10157.61       0
Bank Sta=9183.813,10554.11
Exp/Cntr=0.3,0.1